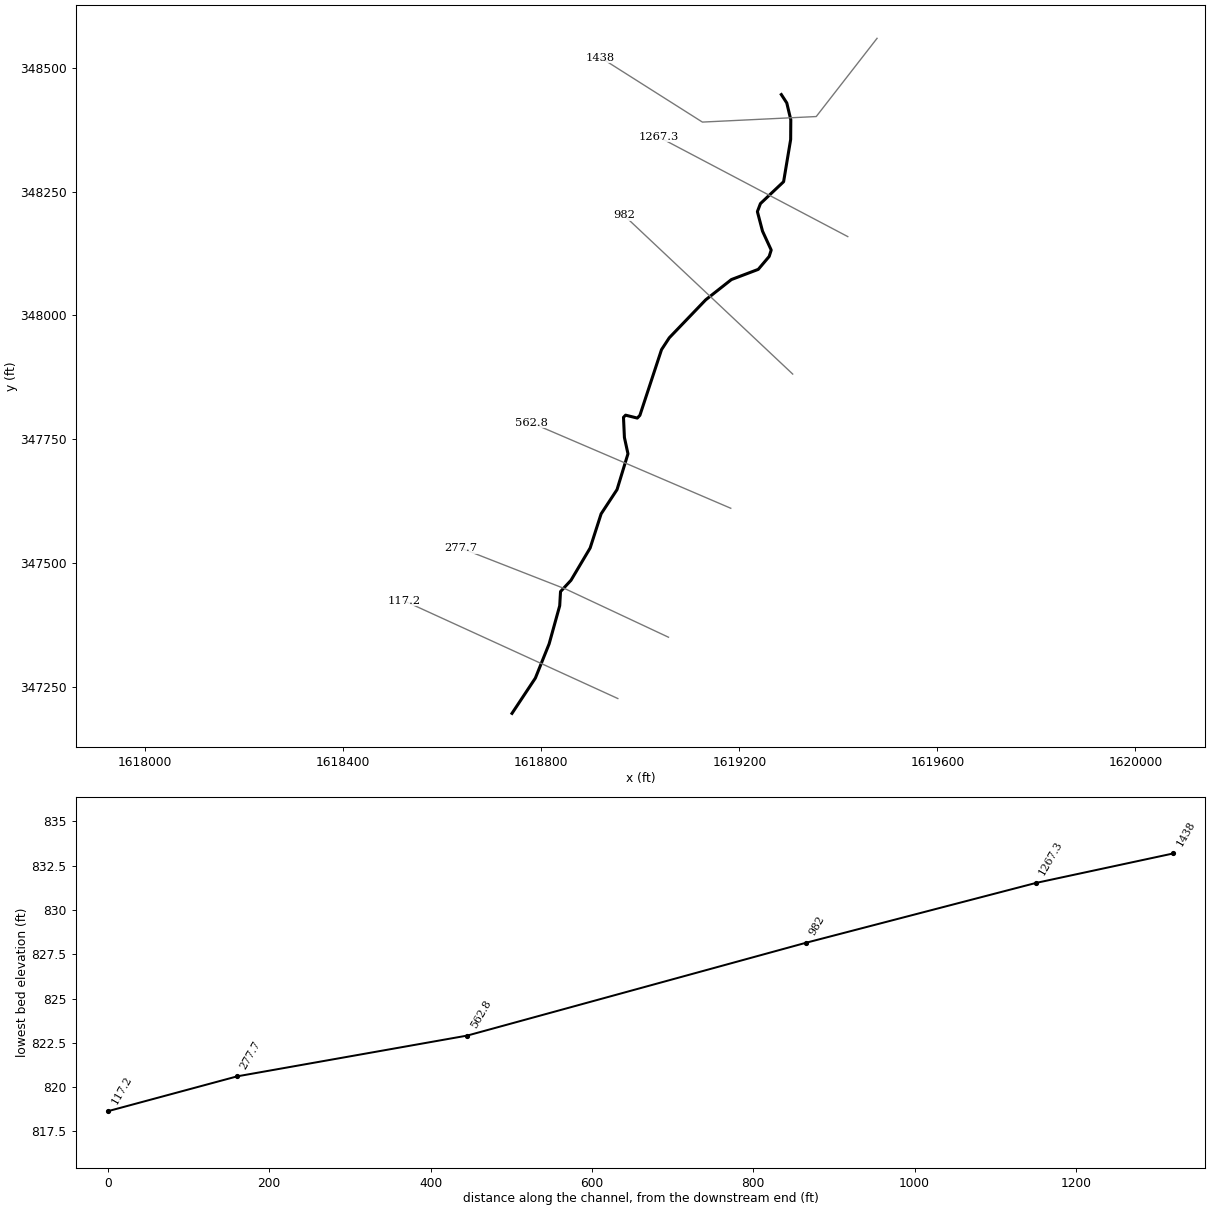
--- mrbrnch.prj (project) ---

Proj Title=mrbrnch
Current Plan=p01
Default Exp/Contr=0,0
English Units
Geom File=g01
Flow File=f01
Plan File=p01
BEGIN DESCRIPTION:
END DESCRIPTION:
DSS Export Rating Curves= 0
DSS Export Rating Curve Sorted= 0
DSS Export Volume Flow Curves= 0
DXF OffsetX= 0
DXF OffsetY= 0
DXF ScaleX= 0
DXF ScaleY= 0

--- mrbrnch.p01 (plan) ---

Plan Title=Approximate Study - 100yr
Program Version=4.00
Geom File=g01
Flow File=f01
Subcritical Flow
K Sum by GR= 0
Std Step Tol= 0.01
Critical Tol= 0.01
Num of Std Step Trials= 20
Max Error Tol= 0.3
Flow Tol Ratio= 0.001
Split Flow NTrial= 30
Split Flow Tol= 0.02
Split Flow Ratio= 0.02
Log Output Level= 0
Friction Slope Method= 1
Unsteady Friction Slope Method= 2
Unsteady Bridges Friction Slope Method= 1
Parabolic Critical Depth
Global Vel Dist= 0 , 0 , 0
Global Log Level= 0
CheckData=True
Encroach Param=-1 ,0,0, 0
Run HTab= 0
Run UNet= 0
Run PostProcess= 0
Run WQNet= 0
UNET Theta= 0
UNET Theta Warmup= 0
UNET ZTol= 0
UNET ZSATol= 0
UNET MxIter= 0
UNET MaxInSteps= 0
UNET DtIC= 0
UNET DtMin= 0
UNET MaxCRTS= 0
UNET WFStab= 0
UNET SFStab= 0
UNET WFX= 1
UNET SFX= 1
UNET DSS MLevel= 1
UNET DZMax Abort= 0
UNET Convert EG Bridges= 0
UNET Use Existing IB Tables= 0
UNET Froude Reduction=False
UNET Froude Limit= 0
UNET Froude Power= 0
UNET Time Slicing=0,0, 5
Write IC File= 0
Echo Input=False
Echo Output=False
Write Detailed= 0
Detailed Automatic Start=False, 0
WQ ULTIMATE=-1
WQ Max Comp Step=1HOUR
WQ Output Interval=15MIN
WQ Output Selected Increments= 0
WQ Output face flow=0
WQ Output face velocity=0
WQ Output face area=0
WQ Output face dispersion=0
WQ Output cell volume=0
WQ Output cell surface area=0
WQ Output cell continuity=0
WQ Output face conc=0
WQ Output face dconc_dx=0
WQ Output face courant=0
WQ Output face peclet=0
WQ Output face adv mass=0
WQ Output face disp mass=0
WQ Output cell mass=0
WQ Output cell source sink temp=0
WQ Output cell source sink nsm=0
WQ Output MaxMinRange=-1
WQ Daily Max Min Mean=-1
WQ Daily Range=0
WQ Daily Time=0
WQ Create Restart=0
WQ Fixed Restart=0
WQ System Summary=False
Sorting and Armoring Iterations= 10
XS Update Threshold= 0.02
Hydraulics Update Threshold= 0.02
Energy Slope Method= 1
Volume Change Method= 0
XS Weighting Method= 0
Number of US Weighted Cross Sections= 1
Number of DS Weighted Cross Sections= 1
Upstream XS Weight=0.25
Main XS Weight=0.5
Downstream XS Weight=0.25
Number of DS XS's Weighted with US Boundary= 1
Upstream Boundary Weight= 1
Weight of XSs Associated with US Boundary= 0
Number of US XS's Weighted with DS Boundary= 1
Downstream Boundary Weight= 0.5
Weight of XSs Associated with DS Boundary= 0.5
Sediment Output Level= 4
Mass or Volume Output= 0
Output Increment Type= 1
Profile and TS Output Increment= 10
XS Output Flag= 0
XS Output Increment= 10
Disregard all LS=0
Disregard all Conn=0
Disregard all Breaches=0
Disregard all Pumps=0

--- mrbrnch.f01 (steady flow) ---

Flow Title=USGS Regression Equation
Program Version=4.00
Number of Profiles= 1
Profile Names=P100yr
River Rch & RM=mrbrnch,Main            ,1438
     355
River Rch & RM=mrbrnch,Main            ,982
     420
River Rch & RM=mrbrnch,Main            ,277.7
     427
Boundary for River Rch & Prof#=mrbrnch,Main            , 1
Up Type= 0
Dn Type= 3
Dn Slope=0.010933
DSS Import GetInterval= 0
DSS Import GetPeak= 0
DSS Import FillOption= 0

--- mrbrnch.g01 (geometry) ---

Geom Title=USGS 3m DEM
Program Version=4.00

River Reach=mrbrnch         ,Main
Reach XY= 30
     1619284.902      348446.102     1619295.896       348429.17
     1619304.007      348395.121      1619303.73      348355.444
     1619289.467      348270.102     1619242.675      348225.904
     1619236.517      348209.685     1619246.878      348170.234
     1619264.459      348132.094     1619260.326      348119.145
      1619238.28       348093.06     1619184.014      348072.464
     1619132.238      348031.628     1619058.578      347954.877
     1619042.892      347930.908     1618999.196      347798.211
     1618993.951      347792.725     1618970.292       347798.59
     1618966.077      347794.188     1618967.962      347753.506
     1618975.121      347720.568      1618953.05      347648.271
      1618920.89      347599.243     1618898.717      347530.243
     1618860.036      347465.075     1618838.913      347442.271
     1618837.247      347413.653     1618815.937      347336.767
     1618788.104      347267.536     1618740.902      347196.274

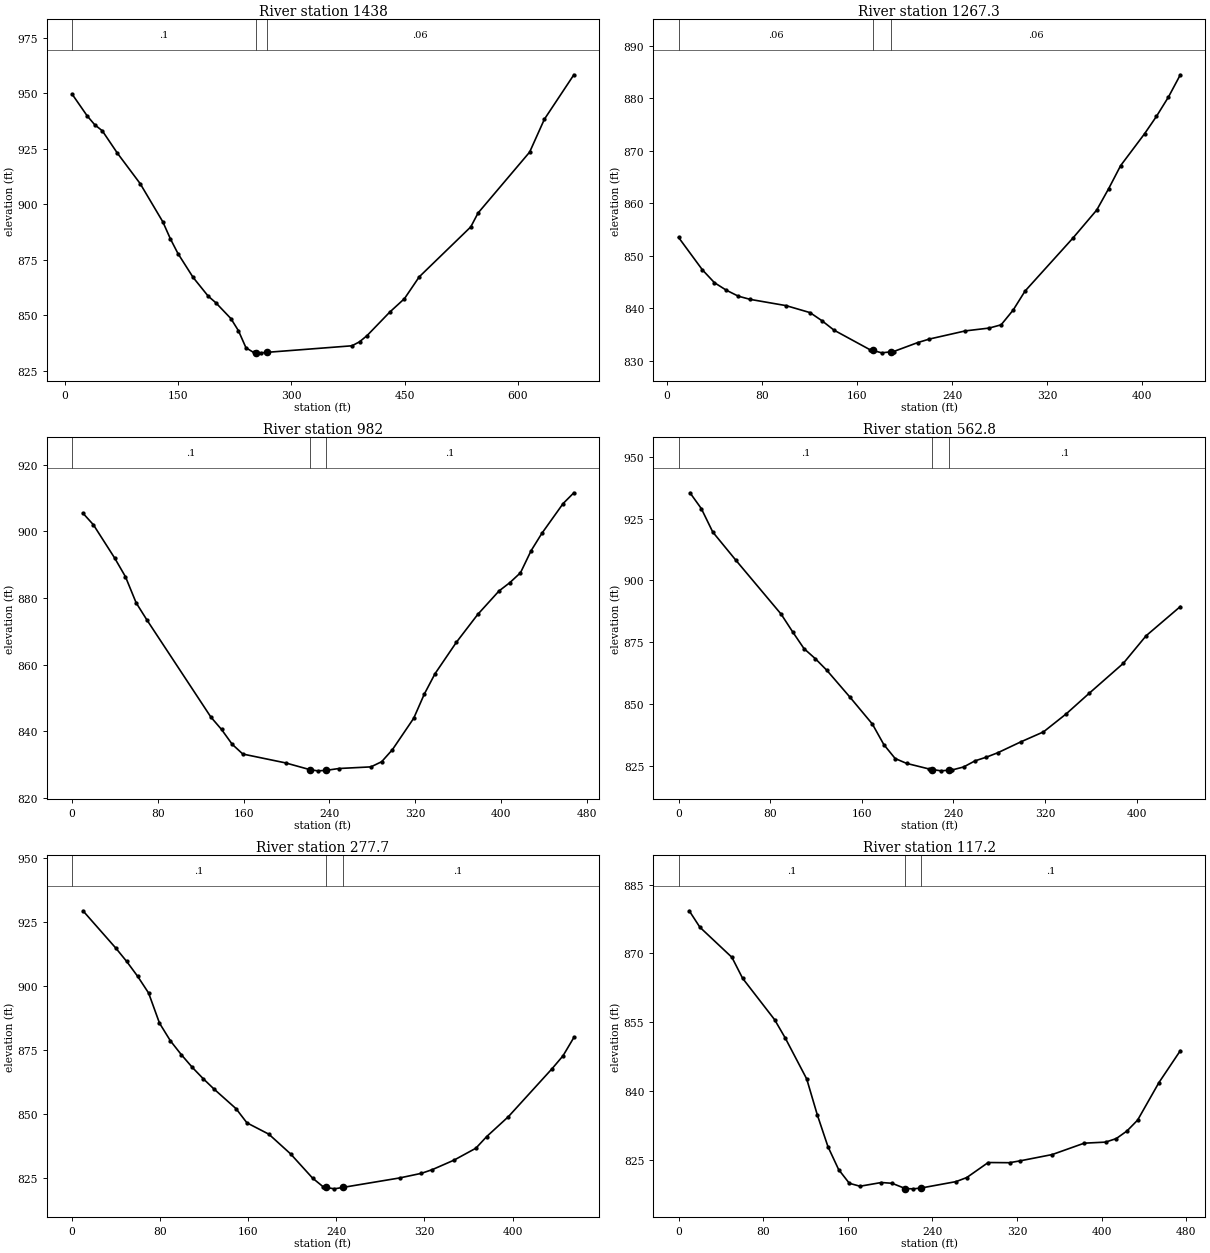
Type RM Length L Ch R = 1 ,1438    ,182.9,170.7,158.4
XS GIS Cut Line= 4
     1619478.213      348559.693     1619355.369      348401.732
      1619125.45      348390.544     1618919.704      348520.923
#Sta/Elev= 30
      10   949.6      30  939.79      40  935.79      50  933.08      70     923
   100.1  909.32   130.1  892.11   140.1  884.46   150.1  877.86   170.1  867.15
   190.1  858.69   200.1  855.76   220.1  848.62   230.1  843.16   240.1  835.46
   250.1  833.38   252.7  833.33   260.2  833.19   267.7  833.41   380.3  836.36
   390.3  838.15   400.3  840.95   430.3  851.51   449.8  857.58   469.3  867.37
   537.5  889.85   547.2  896.12   615.4   923.5   634.9  938.28   673.9  958.28
#Mann= 3 , 0 , 0
      10      .1       0   252.7    .045       0   267.7     .06       0
Bank Sta=252.7,267.7
XS Rating Curve= 0 ,0
Exp/Cntr=0.3,0.1

Type RM Length L Ch R = 1 ,1267.3  ,292,285.3,278.7
XS GIS Cut Line= 2
     1619419.074      348159.239      1619036.84      348360.632
#Sta/Elev= 30
      10  853.51    30.1  847.32    40.2  844.88    50.2  843.45    60.3  842.31
    70.3   841.7   100.5  840.51   120.6  839.18   130.6  837.64   140.7  835.85
   170.8  832.14   173.4  831.98   180.9  831.52   188.4  831.71   190.9  831.77
     211  833.46     221  834.15   251.2   835.7   271.3  836.24   281.3  836.86
   291.4  839.66   301.4  843.28   341.6  853.36   361.7  858.72   371.8  862.82
   381.8  867.18   401.9  873.24   411.9  876.55     422  880.24     432  884.48
#Mann= 3 , 0 , 0
      10     .06       0   173.4    .045       0   188.4     .06       0
Bank Sta=173.4,188.4
XS Rating Curve= 0 ,0
Exp/Cntr=0.3,0.1

Type RM Length L Ch R = 1 ,982     ,396.6,419.2,421.8
XS GIS Cut Line= 2
     1619307.829      347881.625     1618966.969      348202.395
#Sta/Elev= 30
      10  905.51    19.9  901.99    39.8  891.97    49.8   886.4    59.8  878.55
    69.7  873.48   129.5  844.27   139.4  840.57   149.4   836.1   159.3  833.18
   199.2  830.52   221.6  828.52     229  828.14   236.6  828.27     249  828.84
   278.8  829.33   288.8  830.88   298.8  834.48   318.7  843.92   328.6  851.18
   338.6   857.3   358.5  866.72   378.4  875.07   398.3  882.13   408.3   884.6
   418.3  887.58   428.2   894.2   438.2  899.39   458.1  908.37   468.1  911.59
#Mann= 3 , 0 , 0
       0      .1       0   221.6    .045       0   236.6      .1       0
Bank Sta=221.6,236.6
XS Rating Curve= 0 ,0
Exp/Cntr=0.3,0.1

Type RM Length L Ch R = 1 ,562.8   ,285.3,285.1,286.3
XS GIS Cut Line= 2
     1619182.747      347610.548     1618779.962       347783.17
#Sta/Elev= 30
      10  935.41    19.9  929.01    29.9  919.52    49.8  908.27    89.6   886.3
    99.6  879.18   109.6  872.34   119.5  868.27   129.5  863.59   149.4  852.88
   169.3  841.82   179.3  833.51   189.2  827.88   199.2  825.92   219.1  823.63
   221.6  823.45   229.1  822.91   236.6  823.19     239  823.28     249  824.48
   258.9  826.95   268.9  828.46   278.9  830.25   298.8  834.61   318.7  838.67
   338.6  845.98   358.5  854.24   388.4   866.4   408.3  877.55   438.2  889.38
#Mann= 3 , 0 , 0
       0      .1       0   221.6    .045       0   236.6      .1       0
Bank Sta=221.6,236.6
XS Rating Curve= 0 ,0
Exp/Cntr=0.3,0.1

Type RM Length L Ch R = 1 ,277.7   ,160.2,160.5,159.4
XS GIS Cut Line= 3
     1619056.981      347350.066     1618850.276      347446.986
     1618638.518      347529.755
#Sta/Elev= 30
     9.9  929.32    39.7  914.74    49.6  909.51    59.6  903.67    69.5  897.17
    79.4  885.39    89.3  878.48    99.3  873.02   109.2  868.09   119.1  863.67
     129  859.59   148.9  851.96   158.8  846.41   178.7  841.98   198.5  834.25
   218.4  824.81   228.3  821.32   230.7  821.15   238.2  820.61   245.7  821.15
   297.5  824.87   317.3  826.68   327.2  828.13   346.9  831.84   366.7  836.49
   376.6  841.07   396.3  848.85   435.9  867.58   445.8  872.59   455.7  879.78
#Mann= 3 , 0 , 0
       0      .1       0   230.7    .045       0   245.7      .1       0
Bank Sta=230.7,245.7
XS Rating Curve= 0 ,0
Exp/Cntr=0.3,0.1

Type RM Length L Ch R = 1 ,117.2   ,120.7,117.2,113.7
XS GIS Cut Line= 2
     1618954.639      347226.259     1618523.084      347423.541
#Sta/Elev= 30
    10.1  879.29    20.2   875.7    50.5  869.13    60.6  864.56    90.9  855.52
     101   851.5   121.2  842.61   131.2  834.79   141.3  827.84   151.4  822.84
   161.5  819.85   171.6  819.21   191.8  820.02   201.9  819.85   214.6  818.69
   222.1  818.64   229.6  818.83   262.5  820.22   272.6  821.11   292.8  824.38
     313  824.34   323.1  824.75   353.4  826.12   383.6   828.6   403.8  828.83
   413.9   829.6     424  831.25   434.1  833.63   454.3  841.83   474.5  848.78
#Mann= 3 , 0 , 0
       0      .1       0   214.6    .045       0   229.6      .1       0
Bank Sta=214.6,229.6
XS Rating Curve= 0 ,0
Exp/Cntr=0.3,0.1

Chan Stop Cuts=-1
Use User Specified Reach Order=0